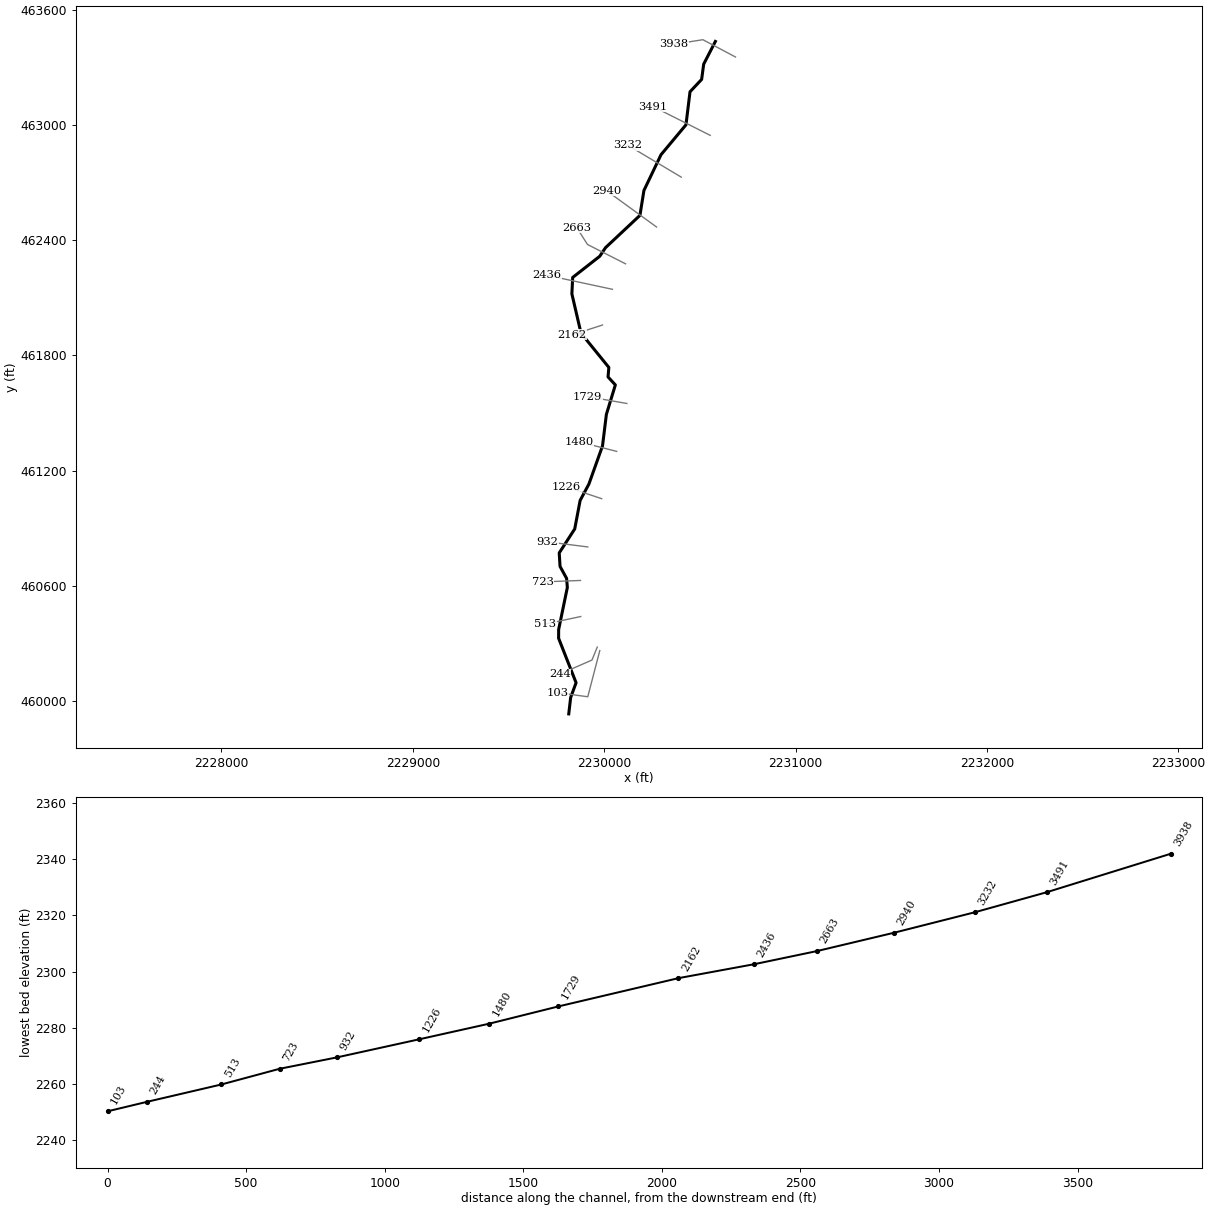
--- INDIANDRFTT1.prj (project) ---

Proj Title=INDIANDRFTT1
Current Plan=p01
Default Exp/Contr=0,0
English Units
Geom File=g01
Flow File=f01
Plan File=p01
Background Map Layer=Inundation Boundary (01pct Value_0)
BEGIN DESCRIPTION:
----------MODEL BY WOOD PLC 2021----------
Stream Name:  Indian Draft Tributary
Flood Zone: Enhanced Approximate
Pocahontas County, WV
HEC-RAS Version: RAS 6.1
Vertical Datum: NAVD88
Projection: NAD 1983 StatePlane West Virginia S FIPS 4702 (US Feet)
Terrain: 1-meter LIDAR (FEMA Region III 3DEP collected 2016-2018)
Land Use: 2019 NLCD
Hydrologic Method:
WV SIR2010-5033 regression equations
Model Notes:
Normal Depth tie in to Indian Draft
END DESCRIPTION:
DSS Export Rating Curves= 0
DSS Export Rating Curve Sorted= 0
DSS Export Volume Flow Curves= 0
DXF OffsetX= 0
DXF OffsetY= 0
DXF ScaleX= 0
DXF ScaleY= 0

--- INDIANDRFTT1.p01 (plan) ---

Plan Title=Floodplain
Program Version=6.10
Short Identifier=Floodplain
Geom File=g01
Flow File=f01
Subcritical Flow
K Sum by GR= 0
Std Step Tol= 0.01
Critical Tol= 0.01
Num of Std Step Trials= 20
Max Error Tol= 0.3
Flow Tol Ratio= 0.001
Split Flow NTrial= 30
Split Flow Tol= 0.02
Split Flow Ratio= 0.02
Log Output Level= 0
Friction Slope Method= 1
Unsteady Friction Slope Method= 2
Unsteady Bridges Friction Slope Method= 1
Parabolic Critical Depth
Global Vel Dist= 0 , 0 , 0
Global Log Level= 0
CheckData=False
Encroach Param=-1 ,0,0, 0
Mapping Interval=1HOUR
Computation Time Step Use Courant=        0
Computation Time Step Use Time Series=    0
Computation Time Step Count To Double=0
Computation Time Step Max Doubling=0
Computation Time Step Max Halving=0
Computation Time Step Residence Courant=0
Run HTab= 0
Run UNet= 0
Run Sediment= 0
Run PostProcess= 0
Run WQNet= 0
Run RASMapper=-1
UNET Theta= 0
UNET Theta Warmup= 0
UNET ZTol= 0
UNET ZSATol= 0
UNET MxIter= 0
UNET Max Iter WO Improvement= 0
UNET MaxInSteps= 0
UNET DtIC= 0
UNET DtMin= 0
UNET MaxCRTS= 0
UNET WFStab= 0
UNET SFStab= 0
UNET WFX= 1
UNET SFX= 1
UNET Gravity=32.174
UNET 1D Methodology=Finite Difference
UNET DSS MLevel= 1
UNET Pardiso=0
UNET DZMax Abort= 0
UNET Use Existing IB Tables= 0
UNET Froude Reduction=False
UNET Froude Limit= 0
UNET Froude Power= 0
UNET D1 Cores= 0
UNET WindReference=Eulerian
UNET WindDragFormulation=Hsu (1988)
UNET D2 Coriolis=0
UNET D2 Cores= 0
UNET D2 Theta= 1
UNET D2 Theta Warmup= 1
UNET D2 Z Tol= 0.01
UNET D2 Volume Tol= 0.01
UNET D2 Max Iterations= 20
UNET D2 Equation= 0
UNET D2 RampUpFraction=0.1
UNET D2 TimeSlices= 1
UNET D2 Turbulence Formulation=Non-Conservative (original)
UNET D2 Eddy Viscosity=0.3
UNET D2 Transverse Eddy Viscosity=0.1
UNET D2 Smagorinsky Mixing=0
UNET D2 BCVolumeCheck=0
UNET D2 Cores=0
UNET D2 SolverType=PARDISO (Direct)
UNET D2 Minimum Iterations= 2147483647
UNET D2 Maximum Iterations= 2147483647
UNET D2 Restart Number= 10
UNET D2 Relaxation Coeff=1.3
UNET D2 SOR Precondition Iterations= 10
UNET D2 ILUT Maximum Fill= 8
UNET D2 ILUT Tolerance=1E-08
UNET D1D2 MaxIter= 0
UNET D1D2 ZTol=0.01
UNET D1D2 QTol=0.1
UNET D1D2 MinQTol=1
Write IC File= 0
Write IC File at Fixed DateTime=0
Write IC File at Sim End=0
Echo Input=False
Echo Parameters=False
Echo Output=False
Write Detailed= 0
HDF Write Warmup=0
HDF Write Time Slices=0
HDF Flush=0
HDF Compression= 1
HDF Chunk Size= 1
HDF Spatial Parts= 1
HDF Use Max Rows=0
HDF Fixed Rows= 1
Calibration Method= 0
Calibration Iterations= 20
Calibration Max Change=0.05
Calibration Tolerance=0.2
Calibration Maximum=1.5
Calibration Minimum=0.5
Calibration Optimization Method= 1
WQ AD Non Conservative
WQ ULTIMATE=-1
WQ Max Comp Step=1HOUR
WQ Output Interval=15MIN
WQ Output Selected Increments= 0
WQ Output face flow=0
WQ Output face velocity=0
WQ Output face area=0
WQ Output face dispersion=0
WQ Output cell volume=0
WQ Output cell surface area=0
WQ Output cell continuity=0
WQ Output cumulative cell continuity=0
WQ Output face conc=0
WQ Output face dconc_dx=0
WQ Output face courant=0
WQ Output face peclet=0
WQ Output face adv mass=0
WQ Output face disp mass=0
WQ Output cell mass=0
WQ Output cell source sink temp=0
WQ Output nsm pathways=0
WQ Output nsm derived pathways=0
WQ Create Restart=0
WQ Fixed Restart=0
WQ System Summary=0
WQ Write To DSS=0
Sorting and Armoring Iterations= 10
XS Update Threshold= 0.02
Bed Roughness Predictor= 0
Hydraulics Update Threshold= 0.02
Energy Slope Method= 1
Volume Change Method= 1
Sediment Retention Method= 0
Sediment TS Multiplier= 1
Warm Up Method= 0
XS Weighting Method= 0
Number of US Weighted Cross Sections= 1
Number of DS Weighted Cross Sections= 1
Upstream XS Weight=0
Main XS Weight=1
Downstream XS Weight=0
Number of DS XS's Weighted with US Boundary= 1
Upstream Boundary Weight= 1
Weight of XSs Associated with US Boundary= 0
Number of US XS's Weighted with DS Boundary= 1
Downstream Boundary Weight= 0.5
Weight of XSs Associated with DS Boundary= 0.5
Percentile Method= 0
Sediment Output Level= 3
Mass or Volume Output= 0
Output Increment Type= 1
Profile and TS Output Increment= 1
Transport Output Increment 1
XS Output Flag= 0
XS Output Increment= 10
Read HDF5 Sediment Hotstart= 0
Sediment Hotstart Type= 0
Write Gradation File= 0
Read Gradation Hotstart= 0
Write HDF5 File= 1
Write Binary Output= 1
Write DSS Sediment File= 0
DSS Sediment Output Type= 1
SV Curve= 0
Specific Gage Flag= 0
Subcell Erosion Methods= 0
Subcell Deposition Methods= 0
Advection Scheme= 1
Matrix Solver= 0
Implicit Weighting Factor= 1
Maximum Outer Loop Convergence Iterations= 5
Convergence Maximum Absolute= 0.001
Convergence RMSE= 0.0001
Grain Fractions Max Abs Error= 0.001
Max Subgrid Regions= 1
Max Subgrid Length Scale= 3.402823E+38
Initial Layer Thickness= 3.402823E+38
Min Layer Thickness= 3.402823E+38
Max Layer Thickness= 3.402823E+38
Number of Layers= 5

--- INDIANDRFTT1.f01 (steady flow) ---

Flow Title=Flow
Program Version=6.10
Number of Profiles= 6
Profile Names=01pct,10pct,04pct,02pct,0_2pct,01plus
River Rch & RM=INDIANDRFTT1,Main            ,3938
     604     320     425     512     843     893
Boundary for River Rch & Prof#=INDIANDRFTT1,Main            , 1
Up Type= 0
Dn Type= 3
Dn Slope=0.04157
Boundary for River Rch & Prof#=INDIANDRFTT1,Main            , 2
Up Type= 0
Dn Type= 3
Dn Slope=0.04157
Boundary for River Rch & Prof#=INDIANDRFTT1,Main            , 3
Up Type= 0
Dn Type= 3
Dn Slope=0.04157
Boundary for River Rch & Prof#=INDIANDRFTT1,Main            , 4
Up Type= 0
Dn Type= 3
Dn Slope=0.04157
Boundary for River Rch & Prof#=INDIANDRFTT1,Main            , 5
Up Type= 0
Dn Type= 3
Dn Slope=0.04157
Boundary for River Rch & Prof#=INDIANDRFTT1,Main            , 6
Up Type= 0
Dn Type= 3
Dn Slope=0.04157
DSS Import GetInterval= 0
DSS Import GetPeak= 0
DSS Import FillOption= 0

--- INDIANDRFTT1.g01 (geometry) ---

Geom Title=Geometry
Program Version=6.10

River Reach=INDIANDRFTT1    ,Main
Reach XY= 30
     2230580.916      463434.156     2230519.847      463315.889
     2230509.167      463236.483 2230448.4374847463172.167495437
     2230427.243      462999.9222230296.99879128462844.624479734
     2230207.643      462658.207     2230186.792      462528.534
     2230007.004      462360.5682229976.75900647462315.760325646
 2229835.3850866462205.399566993     2229831.192      462119.991
2229878.77602206461915.824263599 2230024.3564032461737.028029685
2230020.10955016461687.5534271272230058.35409885461645.888857023
     2230011.439      461492.491     2229991.217      461328.297
     2229920.174      461129.9422229874.29369228      461044.448
2229846.05519698460896.0993605122229765.06739596460771.256505173
2229769.39439781460701.018329647     2229803.598      460638.543
     2229807.491      460591.376     2229762.117      460372.602
     2229761.831      460327.0592229853.11078706460095.477386845
2229824.74307538460018.070119747     2229814.839      459933.257

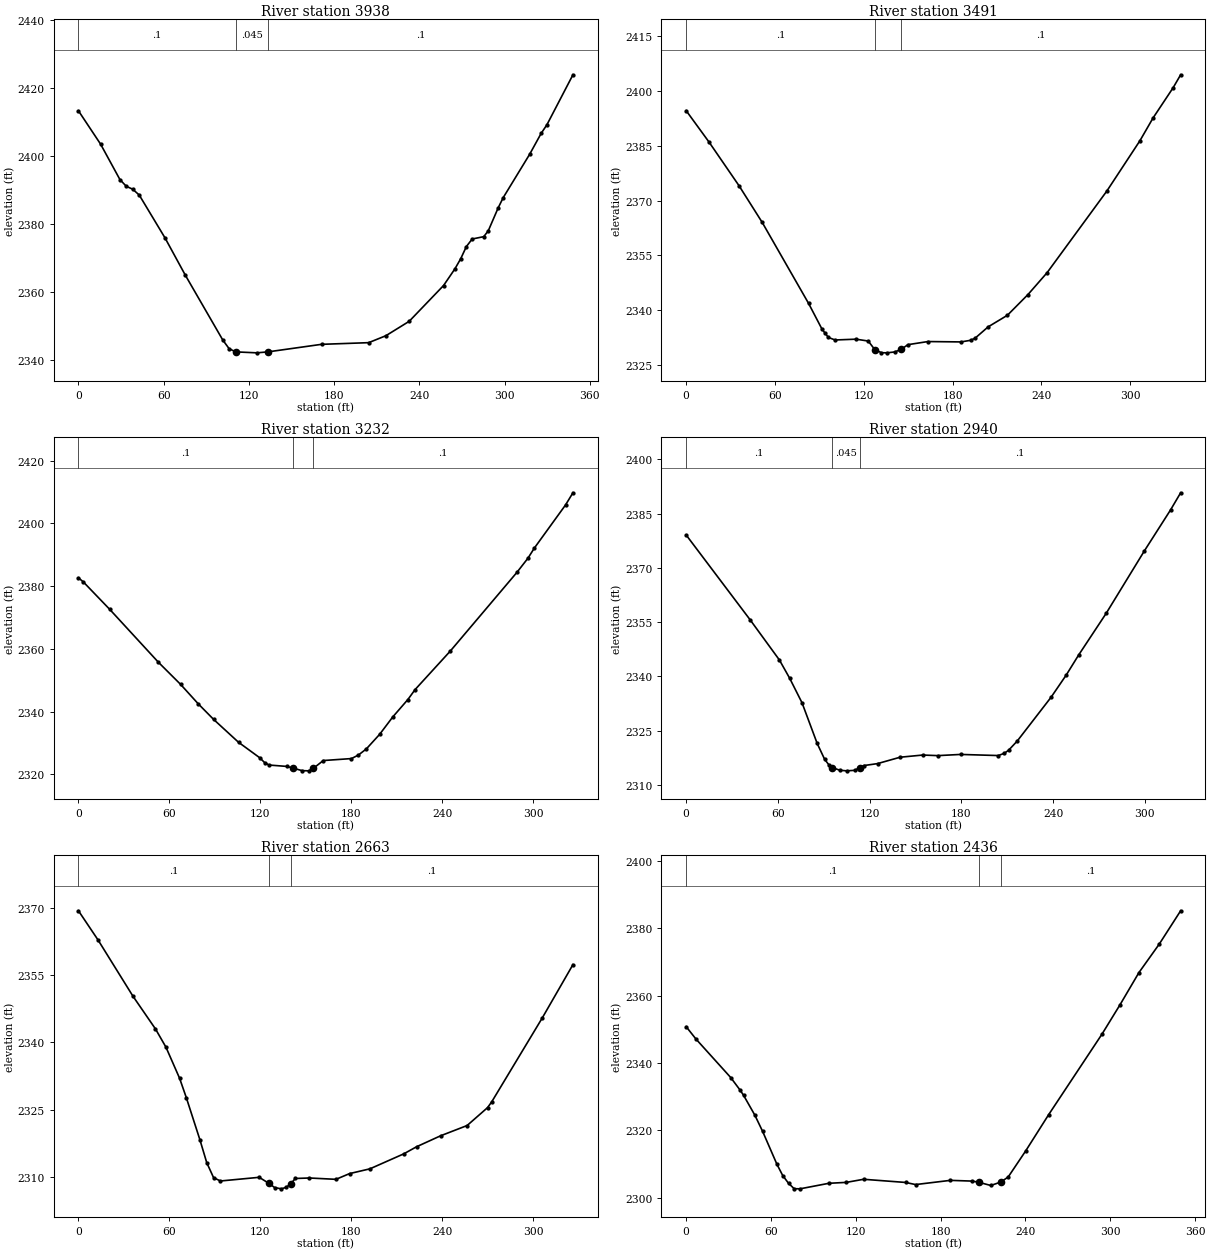
Type RM Length L Ch R = 1 ,3938    ,447,447,447
XS GIS Cut Line= 3
2230685.98033223 463353.201298622230515.69859924463443.232787282
 2230362.1022013463419.173835598
#Sta/Elev= 30
       0 2413.17    15.6 2403.36    29.2 2392.95    33.7 2390.97    38.2 2390.12
    42.8  2388.4    60.9 2375.83    75.3  2364.8   101.6 2345.79   106.1 2343.22
   110.8  2342.3   125.6 2342.02   133.3  2342.3   171.1 2344.52   204.3 2345.01
   216.4 2347.05   232.8 2351.28     257  2361.8     265  2366.7   269.1 2369.69
   273.1 2373.28   277.2 2375.49   285.3 2376.17   288.5  2377.9   295.5 2384.67
     299 2387.64   317.6 2400.37   325.7 2406.52   329.8 2409.08   348.1 2423.76
#Mann= 3 ,-1,0
       0      .1       0   110.8    .045       0   133.3      .1       0
Bank Sta=110.8,133.3
XS Rating Curve= 0 ,0
Exp/Cntr=0.3,0.1

Type RM Length L Ch R = 1 ,3491    ,258.4,259,256.2
XS GIS Cut Line= 2
 2230554.0668571462945.1592210772230255.60089554463095.021876881
#Sta/Elev= 30
       0 2394.61    15.5 2385.98    35.7 2374.06    51.4 2363.99    82.7 2341.83
    91.6 2334.91    93.8 2333.69    96.1 2332.51   100.6 2331.82   114.7 2332.04
     123 2331.53   127.4 2329.19   131.9 2328.34   135.5  2328.3   140.9 2328.54
   145.3 2329.28   149.8 2330.54   163.3 2331.39   185.6 2331.29   192.1 2331.73
   195.1 2332.29     204 2335.42     217 2338.59   230.9 2344.27   243.8 2350.25
   284.1 2372.57   306.5 2386.38   315.4 2392.63   328.9 2400.87     334 2404.43
#Mann= 3 ,-1,0
       0      .1       0   127.4    .045       0   145.3      .1       0
Bank Sta=127.4,145.3
XS Rating Curve= 0 ,0
Exp/Cntr(USF)=0,0
Exp/Cntr=0.3,0.1

Type RM Length L Ch R = 1 ,3232    ,293.7,292,290.3
XS GIS Cut Line= 2
2230402.92348586462727.5620511222230122.58030576462894.423689368
#Sta/Elev= 30
       0 2382.67     3.2 2381.37    20.7 2372.58    52.8 2355.73    67.4  2348.7
    79.1 2342.47    89.2 2337.53   105.6 2330.26   119.6 2325.32   122.8 2323.79
   125.7 2323.01   137.4 2322.57   141.2 2322.08   147.5 2321.22   151.8 2321.16
   154.9 2321.93   161.5 2324.44   180.1 2325.07   184.7  2326.2   189.9 2328.14
   198.7  2332.8   207.4 2338.37   217.3 2343.88   222.1 2347.07   245.3 2359.33
   289.2 2384.38   296.5 2388.91   300.8 2392.19   321.3 2405.88   326.2 2409.77
#Mann= 3 ,-1,0
       0      .1       0   141.2    .045       0   154.9      .1       0
Bank Sta=141.2,154.9
XS Rating Curve= 0 ,0
Exp/Cntr=0.3,0.1

Type RM Length L Ch R = 1 ,2940    ,274.9,277,278.2
XS GIS Cut Line= 2
2230273.56548683462468.0764532682230011.47425951462657.775895806
#Sta/Elev= 30
       0 2379.11    41.9 2355.61      61 2344.52    67.7 2339.48    75.8 2332.67
    85.7 2321.44    90.6 2317.02    93.4 2315.49    95.5 2314.76   100.5 2314.01
   104.9 2313.84   110.3 2313.98   113.5 2314.75   116.4 2315.31   125.2 2315.84
     140 2317.61   154.8 2318.21   164.7 2318.05   179.5 2318.38   204.2 2318.07
     208 2318.67   210.9 2319.52   216.6 2322.09   238.7 2334.19   248.6 2340.32
   256.7 2345.85   274.8 2357.44   299.7 2374.66   316.9 2386.05   323.5 2390.79
#Mann= 3 ,-1,0
       0      .1       0    95.5    .045       0   113.5      .1       0
Bank Sta=95.5,113.5
XS Rating Curve= 0 ,0
Exp/Cntr=0.3,0.1

Type RM Length L Ch R = 1 ,2663    ,222.7,227,230.2
XS GIS Cut Line= 3
2230111.63893979462276.4030484732229912.66163208462377.151052375
2229857.25022993462464.046205741
#Sta/Elev= 30
       0 2369.34    12.8 2362.89    35.9 2350.31    50.8 2342.98    57.7 2338.92
    66.7 2331.98    71.1 2327.69    80.1 2318.26    84.6 2313.16    89.1 2309.82
    93.6 2309.07   119.2 2309.89   125.7 2308.52   129.4  2307.6   133.9 2307.32
   137.1 2307.68   140.1 2308.48     143 2309.63   152.3 2309.74   169.8 2309.44
   178.8 2310.72   192.2 2311.78   214.5 2315.12     223 2316.71   238.8 2319.15
   256.3 2321.44   269.8 2325.44   272.6 2326.76   305.8  2345.4   326.1 2357.33
#Mann= 3 ,-1,0
       0      .1       0   125.7    .045       0   140.1      .1       0
Bank Sta=125.7,140.1
XS Rating Curve= 0 ,0
Exp/Cntr(USF)=0,0
Exp/Cntr=0.3,0.1

Type RM Length L Ch R = 1 ,2436    ,266.4,273.4,279.8
XS GIS Cut Line= 2
2230042.93738654 462143.765952782229700.80226146462216.824197659
#Sta/Elev= 30
       0 2350.82     6.9 2347.16    31.5 2335.71    38.2 2331.94    40.6 2330.43
    48.6 2324.51    54.1 2319.69    64.2 2309.93    68.3 2306.58    72.4 2304.28
    76.4 2302.66    80.5 2302.62     101 2304.27   113.3 2304.54   125.5 2305.46
   155.2 2304.52   162.3 2303.89   186.9 2305.14   202.4 2304.92206.88532304.581
   215.5 2303.62  222.512304.631   227.8 2306.14   240.1 2313.84   256.4 2324.65
   294.1 2348.56   306.9 2357.32   320.3  2366.9   334.6 2375.32   349.8 2385.26
#Mann= 3 ,-1,0
       0      .1       0206.8853    .045       0  222.51      .1       0
Bank Sta=206.8853,222.51
XS Rating Curve= 0 ,0
Exp/Cntr=0.3,0.1

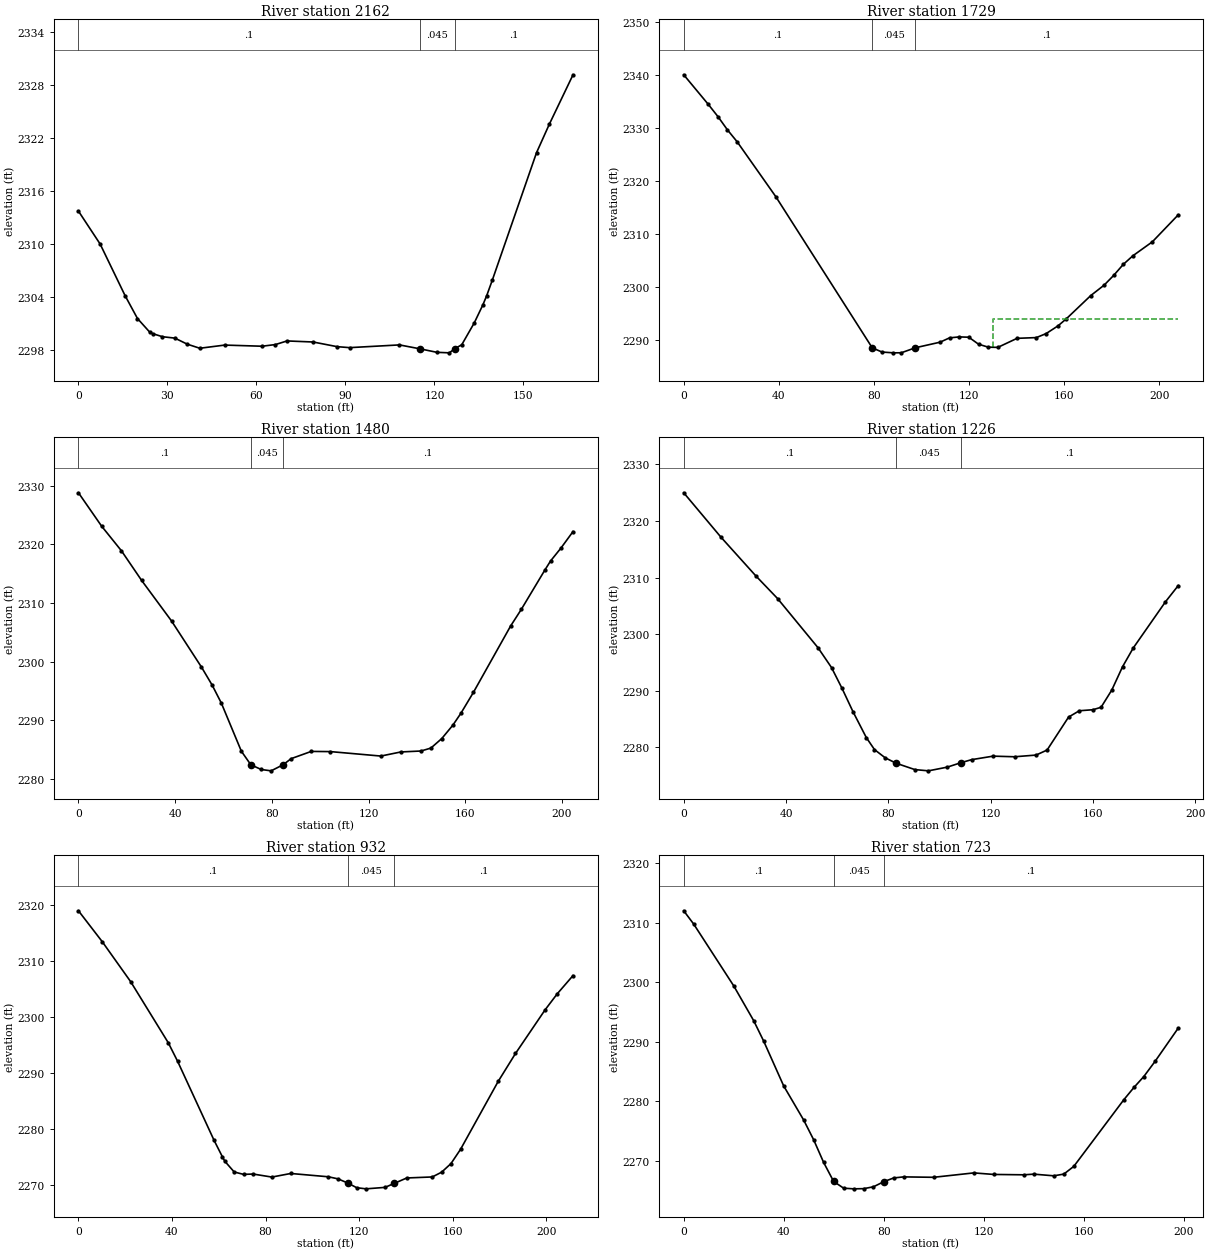
Type RM Length L Ch R = 1 ,2162    ,426.1,433.3,411.2
XS GIS Cut Line= 2
2229991.11440688461957.8406826892229832.47257002461906.612589535
#Sta/Elev= 30
       0 2313.72     7.3 2309.99    15.7 2304.14    19.9 2301.53    24.1 2299.96
    25.1 2299.81    28.3 2299.47    32.5 2299.31    36.7 2298.62    40.9 2298.16
    49.3 2298.52    61.9 2298.39    66.4 2298.58    70.3 2298.99    79.1 2298.87
    87.2 2298.34    91.4 2298.23   108.2 2298.54   115.12298.096   120.8  2297.7
     125 2297.64   126.8  2298.1   129.2 2298.56   133.4 2301.03   136.3 2303.07
   137.6 2304.12   139.5 2305.89   154.4 2320.35   158.7 2323.57   166.7 2329.19
#Mann= 3 ,-1,0
       0      .1       0   115.1    .045       0   126.8      .1       0
Bank Sta=115.1,126.8
XS Rating Curve= 0 ,0
Exp/Cntr(USF)=0,0
Exp/Cntr=0.3,0.1

Type RM Length L Ch R = 1 ,1729    ,250.3,249.4,248.7
XS GIS Cut Line= 2
2230118.34314397 461549.360567492229913.43077136461584.889728871
#Sta/Elev= 30
       0 2340.07    10.3  2334.5    14.4 2332.17    18.4 2329.66    22.5  2327.4
    38.7 2317.07    79.3 2288.49    83.4  2287.7    88.2 2287.55    91.5 2287.56
   97.41 2288.51   107.8 2289.56   111.8 2290.38   115.9 2290.56   119.9  2290.5
     124 2289.18   128.1 2288.62   132.1 2288.58   140.2 2290.29   148.3 2290.43
   152.4 2291.18   157.4 2292.64   160.9 2293.97   171.2 2298.37   176.8 2300.33
   180.8 2302.16   184.9 2304.27   188.9 2305.88   197.1 2308.52     208 2313.62
#Mann= 3 ,0,0
       0      .1       0    79.3    .045       0   97.41      .1       0
#XS Ineff= 2 , 0
                             130            2294
Permanent Ineff=
       F       F
Bank Sta=79.3,97.41
XS Rating Curve= 0 ,0
Exp/Cntr(USF)=0,0
Exp/Cntr=0.3,0.1

Type RM Length L Ch R = 1 ,1480    ,254.4,253.5,253.4
XS GIS Cut Line= 2
2230065.46253169461299.8301782572229867.16023561461350.232011844
#Sta/Elev= 30
       0 2328.79     9.6 2323.09    17.8 2318.89    26.1 2313.87    38.5 2306.94
    50.9 2299.07    55.3 2296.01    59.1 2292.95    67.4 2284.73    71.3 2282.43
    75.6 2281.62    79.7 2281.39   84.632282.418      88 2283.47    96.3  2284.7
   104.2 2284.67   125.1 2283.91   133.4 2284.61   141.7 2284.77   145.8 2285.27
   150.3 2286.89   154.9 2289.18   158.2 2291.19   163.4 2294.77   178.8 2306.09
   183.2 2308.91     193 2315.65   195.3 2317.16   199.6 2319.36   204.6 2322.18
#Mann= 3 ,-1,0
       0      .1       0    71.3    .045       0   84.63      .1       0
Bank Sta=71.3,84.63
XS Rating Curve= 0 ,0
Exp/Cntr(USF)=0,0
Exp/Cntr=0.3,0.1

Type RM Length L Ch R = 1 ,1226    ,291.3,294.6,297.2
XS GIS Cut Line= 2
2229986.96787282461053.6048272922229803.53824895 461114.74803525
#Sta/Elev= 30
       0 2324.99    14.5 2317.17    28.2 2310.29    36.7 2306.28    52.5 2297.59
    57.8 2294.07    61.9  2290.4    66.2 2286.26    71.4 2281.69    74.6 2279.56
    78.8  2278.1    83.1 2277.14    90.4 2276.02    95.7  2275.8   103.1 2276.46
   108.4 2277.24   112.6 2277.78     121  2278.4   129.4 2278.29   137.8 2278.59
   142.1 2279.48   150.5 2285.31   154.7 2286.43     160 2286.61   163.2 2287.04
   167.4 2290.09   171.6 2294.21   175.8 2297.54   188.4 2305.71   193.4 2308.58
#Mann= 3 ,-1,0
       0      .1       0    83.1    .045       0   108.4      .1       0
Bank Sta=83.1,108.4
XS Rating Curve= 0 ,0
Exp/Cntr(USF)=0,0
Exp/Cntr=0.3,0.1

Type RM Length L Ch R = 1 ,932     ,201.8,208.7,206
XS GIS Cut Line= 2
2229914.25703093460802.4219189252229704.38710091460828.862225069
#Sta/Elev= 30
       0    2319    10.2 2313.47    22.3 2306.37    38.4 2295.46    42.4 2292.15
      58 2278.04    61.6 2275.07    62.6 2274.31    66.6  2272.4    70.6 2271.97
    74.7 2272.03    82.7 2271.49    90.8 2272.13   106.9 2271.54     111 2271.17
   115.3  2270.4     119 2269.59     123 2269.39   131.1 2269.65   135.1 2270.37
   140.4 2271.33   151.3 2271.51   155.3 2272.36   159.3 2273.89   163.4 2276.44
   179.5 2288.56   186.9 2293.54   199.6 2301.35   204.8 2304.21   211.5 2307.44
#Mann= 3 ,-1,0
       0      .1       0   115.3    .045       0   135.1      .1       0
Bank Sta=115.3,135.1
XS Rating Curve= 0 ,0
Exp/Cntr(USF)=0,0
Exp/Cntr=0.3,0.1

Type RM Length L Ch R = 1 ,723     ,207.4,210.1,214.4
XS GIS Cut Line= 2
2229876.14048067 460627.913834632229678.42252301460620.357734338
#Sta/Elev= 30
       0 2312.04       4  2309.8      20 2299.42      28 2293.56      32 2290.12
      40 2282.59      48 2276.85      52 2273.53      56 2269.71      60 2266.52
      64 2265.39      68 2265.28      72 2265.31    75.9 2265.62      80 2266.47
      84 2267.11      88 2267.29     100 2267.22   116.1 2267.96   124.1  2267.7
   136.1 2267.64   140.1 2267.75   148.1 2267.47   152.1 2267.76   156.1 2269.06
   176.1 2280.26   180.2 2282.35   184.1 2284.16   188.6 2286.71   197.9 2292.32
#Mann= 3 ,-1,0
       0      .1       0      60    .045       0      80      .1       0
Bank Sta=60,80
XS Rating Curve= 0 ,0
Exp/Cntr(USF)=0,0
Exp/Cntr=0.3,0.1

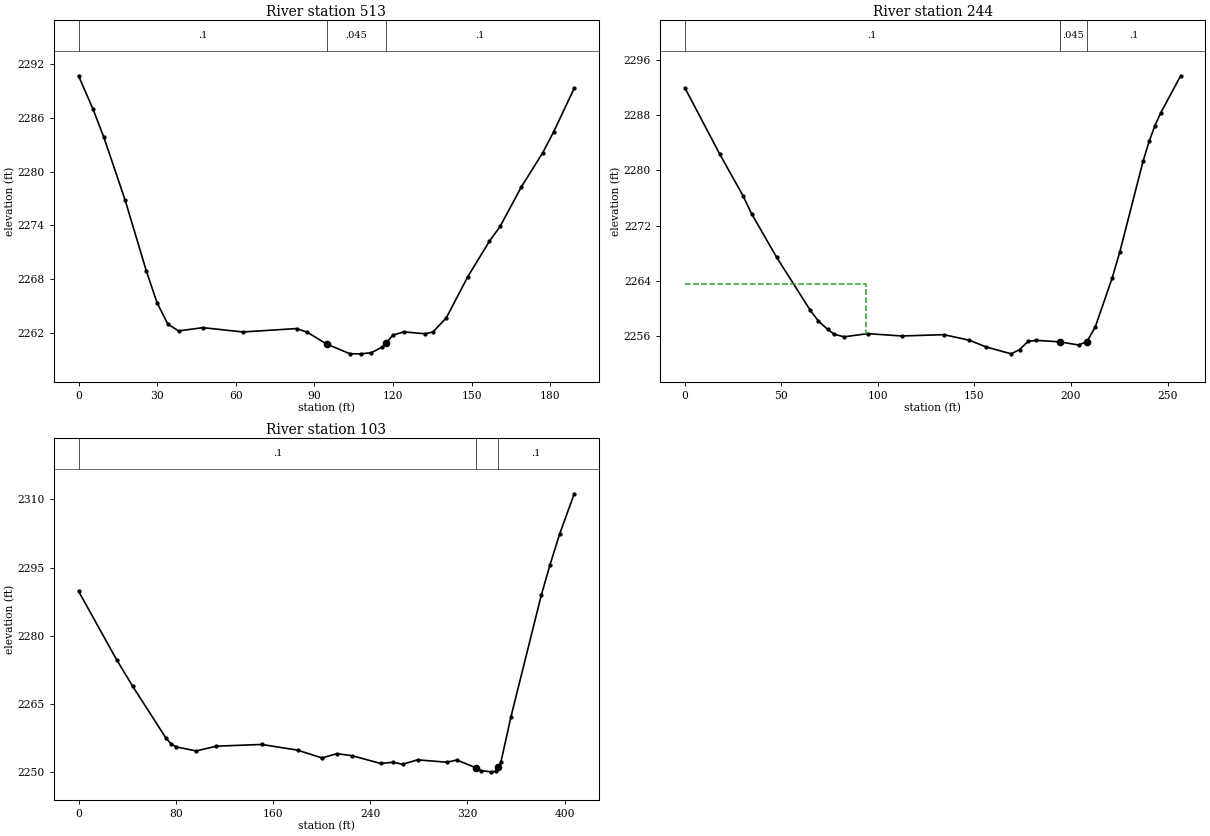
Type RM Length L Ch R = 1 ,513     ,267.3,268.6,269.7
XS GIS Cut Line= 2
2229877.55478497460440.1552689362229692.47264196460400.931174512
#Sta/Elev= 30
       0  2290.7     5.5    2287     9.6  2283.9    17.8 2276.82    25.9 2268.91
      30 2265.37    34.1 2262.99    38.2 2262.24    47.5  2262.6    62.7 2262.12
    83.2  2262.5    87.3 2262.09    94.8 2260.76   103.6 2259.69   107.7 2259.68
   111.8 2259.81   115.9 2260.44   117.3 2260.88     120 2261.76   124.1 2262.13
   132.3 2261.92   135.3 2262.12   140.4 2263.71   148.6  2268.3   156.8 2272.23
   160.9 2273.89     169 2278.29   177.2 2282.13   181.3 2284.42   189.2 2289.31
#Mann= 3 ,-1,0
       0      .1       0    94.8    .045       0   117.3      .1       0
Bank Sta=94.8,117.3
XS Rating Curve= 0 ,0
Exp/Cntr(USF)=0,0
Exp/Cntr=0.3,0.1

Type RM Length L Ch R = 1 ,244     ,143.7,141.8,133.8
XS GIS Cut Line= 3
2229963.91939938460281.1105090412229936.17026739460213.571560495
2229767.64470462460140.143334344
#Sta/Elev= 30
       0  2291.9    18.1 2282.31    30.2 2276.27    34.5 2273.74    47.5 2267.44
    64.8 2259.83    69.1 2258.23      74    2257    77.4  2256.3    82.4 2255.94
    94.8  2256.4   112.3 2256.06   134.1 2256.25   147.2 2255.46   155.9 2254.49
     169 2253.48   173.4  2254.1   177.7 2255.27   182.1 2255.43194.10362255.215
   203.9 2254.76208.30362255.251   212.6 2257.39   221.4 2264.49   225.3 2268.22
   237.4 2281.37   240.5 2284.19   243.5 2286.47   246.5  2288.3   256.8 2293.66
#Mann= 3 ,-1,0
       0      .1       0194.1036    .045       0208.3036      .1       0
#XS Ineff= 2 , 0
           93.69 2263.54
Permanent Ineff=
       F       F
Bank Sta=194.1036,208.3036
XS Rating Curve= 0 ,0
Exp/Cntr(USF)=0,0
Exp/Cntr=0.3,0.1

Type RM Length L Ch R = 1 ,103     ,,,
XS GIS Cut Line= 3
2229977.05275802460262.8744216762229914.25703093 460022.43288768
2229756.44145363460043.915636422
#Sta/Elev= 30
       0 2289.83    31.6 2274.63    44.7 2268.87      72  2257.5    76.2 2256.24
    80.3  2255.6    96.8  2254.7   113.4 2255.75   150.6 2256.13   180.2 2254.88
   200.2 2253.17   212.6  2254.1     225 2253.66   248.5 2251.95   258.7 2252.21
   266.8 2251.78   278.9 2252.75   303.1 2252.22   311.2 2252.71   327.2 2250.97
   331.3 2250.37   339.4 2250.11   343.5 2250.23   345.2 2251.07   347.5 2252.28
   355.8 2262.27   380.7 2288.92   387.8 2295.56   395.9 2302.46   407.8 2311.22
#Mann= 3 ,-1,0
       0      .1       0   327.2    .045       0   345.2      .1       0
Bank Sta=327.2,345.2
XS Rating Curve= 0 ,0
Exp/Cntr(USF)=0,0
Exp/Cntr=0.3,0.1
LCMann Table=0

Chan Stop Cuts=-1
Use User Specified Reach Order=0
Composite Channel Slope=5